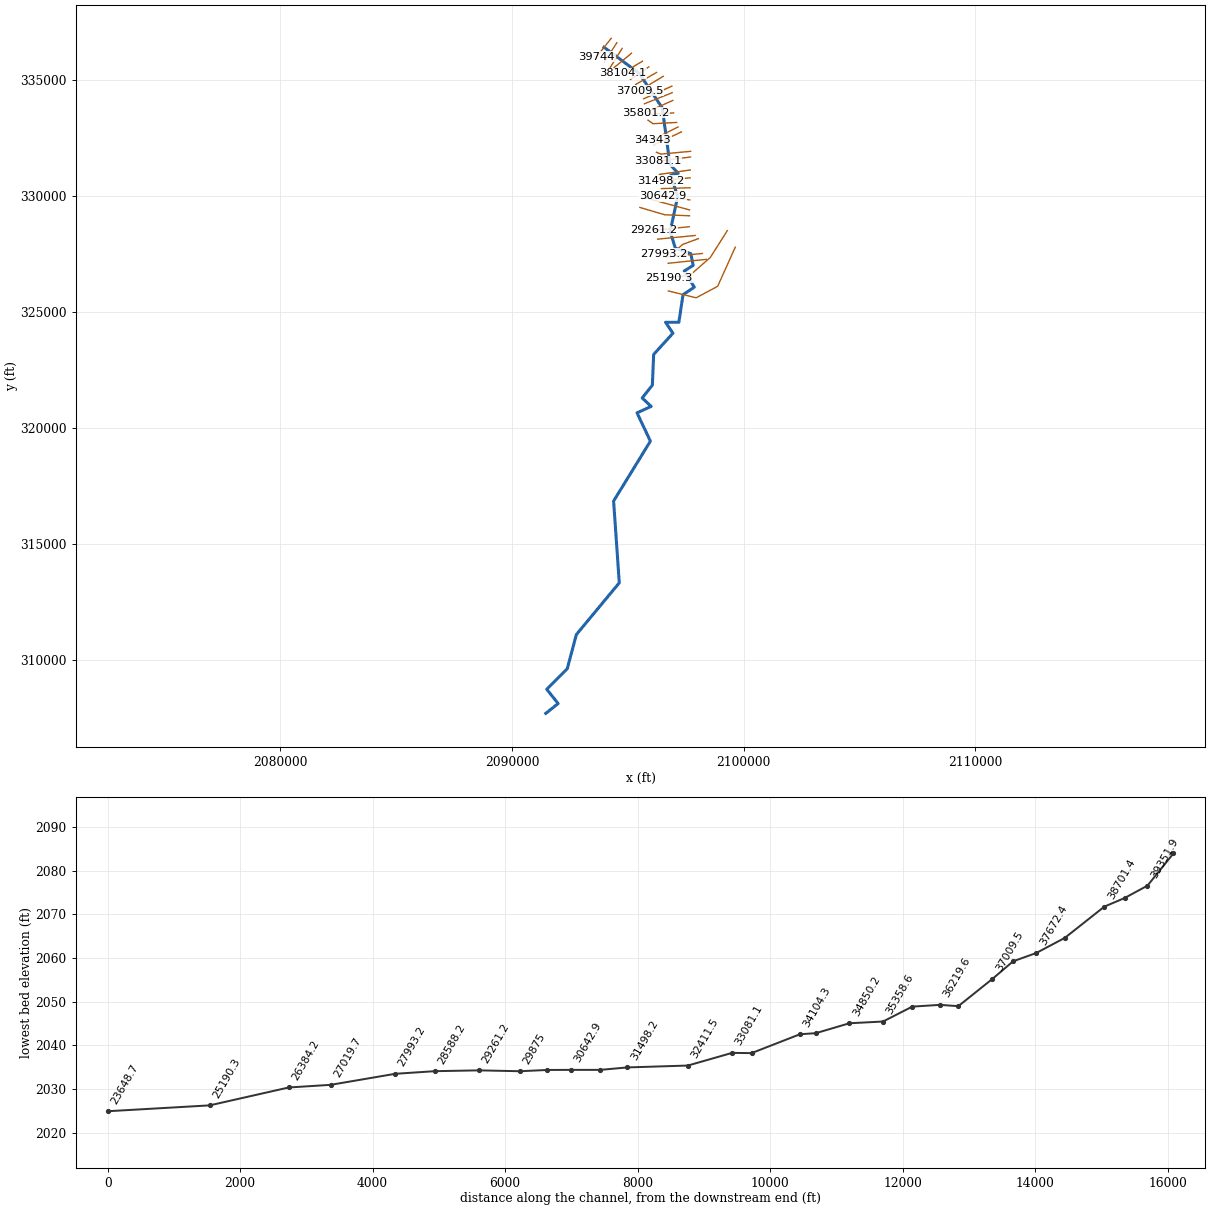
--- HugharCk.prj (project) ---

Proj Title=HugharCk
Current Plan=p01
Default Exp/Contr=0,0
English Units
Geom File=g01
Flow File=f01
Plan File=p01
BEGIN DESCRIPTION:
END DESCRIPTION:
DSS Export Rating Curves= 0
DSS Export Rating Curve Sorted= 0
DSS Export Volume Flow Curves= 0
DXF OffsetX= 0
DXF OffsetY= 0
DXF ScaleX= 0
DXF ScaleY= 0

--- HugharCk.p01 (plan) ---

Plan Title=Floodplain
Program Version=4.00
Geom File=g01
Flow File=f01
K Sum by GR=0
Std Step Tol=0.01
Critical Tol=0.01
Num of Std Step Trials=20
Max Error Tol=0.3
Flow Tol Ratio=0.001
Split Flow NTrial=30
Split Flow Tol=0.02
Split Flow Ratio=0.02
Log Output Level=0
Friction Slope Method=1
Unsteady Friction Slope Method=2
Unsteady Bridges Friction Slope Method=1
Global Log Level=0
CheckData=False
Run HTab=0
Run UNet=0
Run PostProcess=0
UNET Theta=0
UNET Theta Warmup=0
UNET ZTol=0
UNET ZSATol=0
UNET MxIter=0
UNET MaxInSteps=0
UNET DtIC=0
UNET DtMin=0
UNET MaxCRTS=0
UNET WFStab=0
UNET SFStab=0
UNET WFX=0
UNET SFX=0
UNET DSS MLevel=0
UNET DZMax Abort=0
UNET Convert EG Bridges=0
UNET Use Existing IB Tables=0
UNET Froude Limit=0
UNET Froude Power=0
Write IC File=0
Echo Input=False
Echo Output=False
Write Detailed=0

--- HugharCk.f01 (steady flow) ---

Flow Title=NFF Regression Equation
Program Version=4.00
Number of Profiles=1
Profile Names=P100yr
River Rch & RM=HugharCk,Main      ,39744
582.3001
River Rch & RM=HugharCk,Main      ,38104.1
596.3137
River Rch & RM=HugharCk,Main      ,37672.4
867.7750
River Rch & RM=HugharCk,Main      ,34850.2
950.4110
River Rch & RM=HugharCk,Main      ,32411.5
1050.388
River Rch & RM=HugharCk,Main      ,29875
1163.263
River Rch & RM=HugharCk,Main      ,27019.7
1289.943
River Rch & RM=HugharCk,Main      ,16914.3
1420.012
Boundary for River Rch & Prof#=HugharCk,Main      ,1
Up Type=0
Dn Type=3
Dn Slope=0.001461

--- HugharCk.g01 (geometry) ---

Geom Title=USGS 10m DEM
Program Version=4.10

River Reach=HugharCk        ,Main
Reach XY= 30
     2093970.745      336421.767     2095487.725       335293.56
      2096486.34      333801.991     2096814.129      331366.438
     2097174.952      330981.476     2096858.542      330904.602
     2097148.271      329970.156     2096825.564      328470.963
     2097047.902       327755.67     2097715.365       327512.08
     2097818.674      327009.863     2097431.593      326762.138
     2097868.646      326067.173     2097380.773      325741.924
     2097200.362      324550.193     2096624.825      324552.734
     2096946.262      324081.378     2096112.812      323166.616
      2096058.18      321840.212     2095617.316      321285.003
     2096006.397      320922.906      2095395.72       320644.26
     2095972.375      319422.698     2094384.615      316837.144
     2094629.486      313308.197     2092777.995      311077.669
     2092384.299      309601.309     2091498.483      308715.493
     2091990.603      308099.287     2091458.655      307675.057

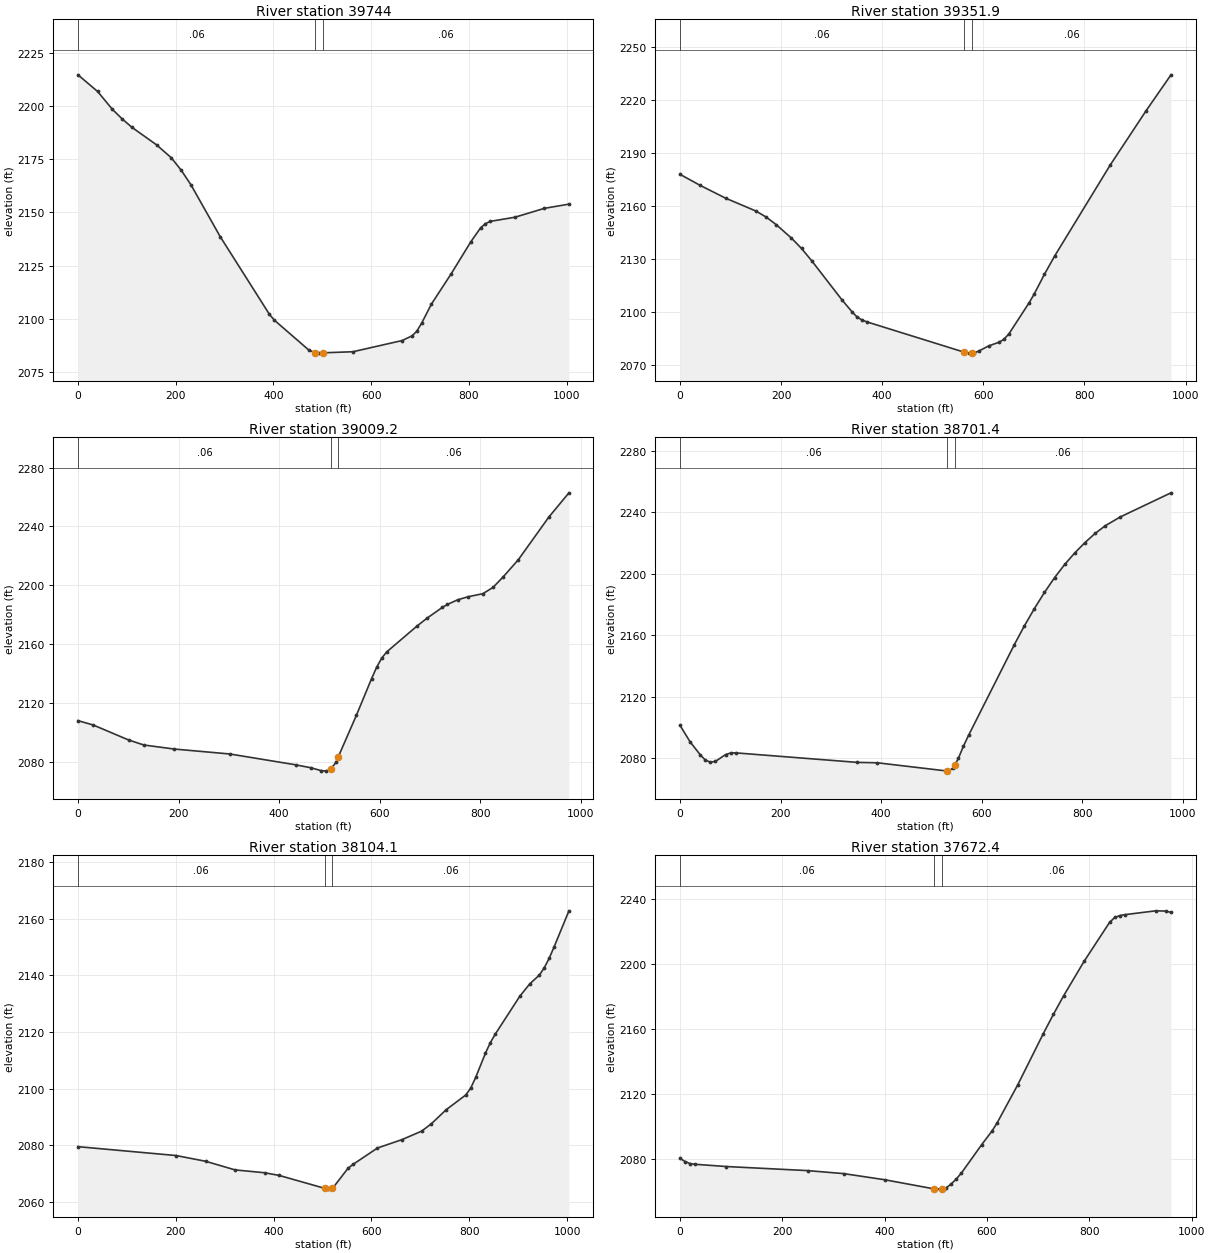
Type RM Length L Ch R = 1 ,39744   ,389.8,392,394.3
XS GIS Cut Line= 2
     2094281.228      336806.204     2093656.491      336019.563
#Sta/Elev= 30
       0 2214.64    40.2 2206.82    70.3 2198.46    90.4 2193.94   110.5 2189.97
   160.7 2181.77   190.9  2175.7     211  2169.9     231 2163.04   291.3 2138.53
   391.8 2102.12   401.8  2099.4   472.1 2085.41   485.4 2084.06   492.2 2083.92
   500.4 2084.06   562.5 2084.57     663 2089.82   683.1 2091.98   693.1 2094.16
   703.2 2098.02   723.3    2107   763.4 2121.12   803.6 2136.15   823.7 2142.75
   833.8 2144.76   843.8 2145.81     894 2147.75   954.3 2151.93  1004.5  2153.9
#Mann= 3 , 0 , 0
       0     .06       0   485.4    .045       0   500.4     .06       0
Bank Sta=485.4,500.4
XS Rating Curve= 0 ,0
Exp/Cntr=0.3,0.1

Type RM Length L Ch R = 1 ,39351.9 ,343.3,342.9,342.6
XS GIS Cut Line= 2
     2094527.427      336616.429     2093994.682      335804.513
#Sta/Elev= 30
       0 2177.95      40 2171.67    90.1 2164.45   150.2 2157.13   170.2 2153.75
   190.2 2149.45   220.2 2141.84   240.3 2135.94   260.3    2129   320.4 2106.72
   340.4 2099.93   350.4 2096.98   360.4 2095.27   370.4  2094.2   562.6 2077.04
   570.6 2076.55   577.6 2076.59   580.6 2076.61   590.7 2077.68   610.7 2080.67
   630.7 2082.69   640.7 2084.37   650.7 2087.55   690.8 2105.24   700.8 2110.22
   720.8 2121.26   740.8 2131.53     851 2183.27     921 2213.66   971.1 2234.39
#Mann= 3 , 0 , 0
       0     .06       0   562.6    .045       0   577.6     .06       0
Bank Sta=562.6,577.6
XS Rating Curve= 0 ,0
Exp/Cntr=0.3,0.1

Type RM Length L Ch R = 1 ,39009.2 ,313.5,307.9,302.2
XS GIS Cut Line= 2
     2094754.143      336373.291     2094235.218      335546.095
#Sta/Elev= 30
       0 2108.03    30.2 2105.09   100.7  2094.9   130.9 2091.49   191.3 2088.74
     302 2085.38   432.9 2078.03   463.1 2076.03   483.2 2074.12   493.3 2073.73
   502.6 2074.95   513.4 2079.81   517.6 2083.31   553.7  2111.6   583.9 2136.51
     594 2144.23     604 2150.45   614.1 2154.74   674.5 2172.34   694.6 2177.72
   724.8 2184.98   734.9    2187     755 2190.08   775.2 2192.15   805.4 2194.29
   825.5 2198.54   845.6 2205.66   875.8 2217.33   936.2 2246.18   976.5  2262.8
#Mann= 3 , 0 , 0
       0     .06       0   502.6    .045       0   517.6     .06       0
Bank Sta=502.6,517.6
XS Rating Curve= 0 ,0
Exp/Cntr=0.3,0.1

Type RM Length L Ch R = 1 ,38701.4 ,600.7,596.6,592.4
XS GIS Cut Line= 2
      2095155.66      336162.169     2094402.531      335540.611
#Sta/Elev= 30
       0 2101.51    20.1 2090.79    40.3 2082.34    50.3 2078.98    60.4 2077.56
    70.5  2078.1    90.6  2082.5   100.7 2083.54   110.7 2083.62   352.3 2077.44
   392.6 2077.17     532 2071.79   533.6 2071.75   543.6 2073.84     547 2075.95
   553.7 2080.12   563.8 2088.06   573.8 2094.96   664.4 2153.66   684.6 2166.01
   704.7 2177.36   724.8 2187.92     745 2197.54   765.1 2206.12   785.2 2213.66
   805.4 2220.33   825.5 2226.26   845.6 2231.25   875.8 2237.04   976.5 2252.69
#Mann= 3 , 0 , 0
       0     .06       0     532    .045       0     547     .06       0
Bank Sta=532,547
XS Rating Curve= 0 ,0
Exp/Cntr=0.3,0.1

Type RM Length L Ch R = 1 ,38104.1 ,428.8,431.6,434.2
XS GIS Cut Line= 2
     2095630.834      335818.581     2094769.425      335303.209
#Sta/Elev= 30
       0 2079.57   200.8 2076.44     261 2074.42   321.2 2071.38   381.4 2070.38
   411.6 2069.42   504.2 2064.89   511.9  2064.6   519.2 2065.03     522  2065.2
   552.1 2071.94   562.1 2073.29   612.3 2079.09   662.5 2082.06   702.7 2085.05
   722.7 2087.67   752.9 2092.61     793 2097.81     803 2100.23   813.1 2103.96
   833.2 2112.57   843.2 2116.27   853.2 2119.25   903.4 2132.62   923.5 2136.92
   943.6 2140.11   953.6 2142.72   963.7 2146.11   973.7 2150.08  1003.8 2162.72
#Mann= 3 , 0 , 0
       0     .06       0   504.2    .045       0   519.2     .06       0
Bank Sta=504.2,519.2
XS Rating Curve= 0 ,0
Exp/Cntr=0.3,0.1

Type RM Length L Ch R = 1 ,37672.4 ,351.4,349.4,347.6
XS GIS Cut Line= 2
     2095906.919      335575.121     2095113.682      335035.046
#Sta/Elev= 30
       0  2080.1      10 2078.14      20 2076.85      30 2076.44      90 2075.08
   249.9 2072.54   319.9  2070.7   399.8 2066.94   497.3 2061.25   499.8 2061.14
   512.3 2061.32   519.8 2061.81   529.8 2064.26   539.8 2067.33   549.8 2070.99
   589.8 2088.63   609.8 2096.94   619.8 2101.98   659.8 2125.24   709.7 2156.77
   729.7  2168.8   749.7 2180.26   789.7 2201.49   839.7 2225.59   849.7 2228.55
   859.7 2229.74   869.7 2230.29   929.6 2232.65   949.6 2232.49   959.6  2231.7
#Mann= 3 , 0 , 0
       0     .06       0   497.3    .045       0   512.3     .06       0
Bank Sta=497.3,512.3
XS Rating Curve= 0 ,0
Exp/Cntr=0.3,0.1

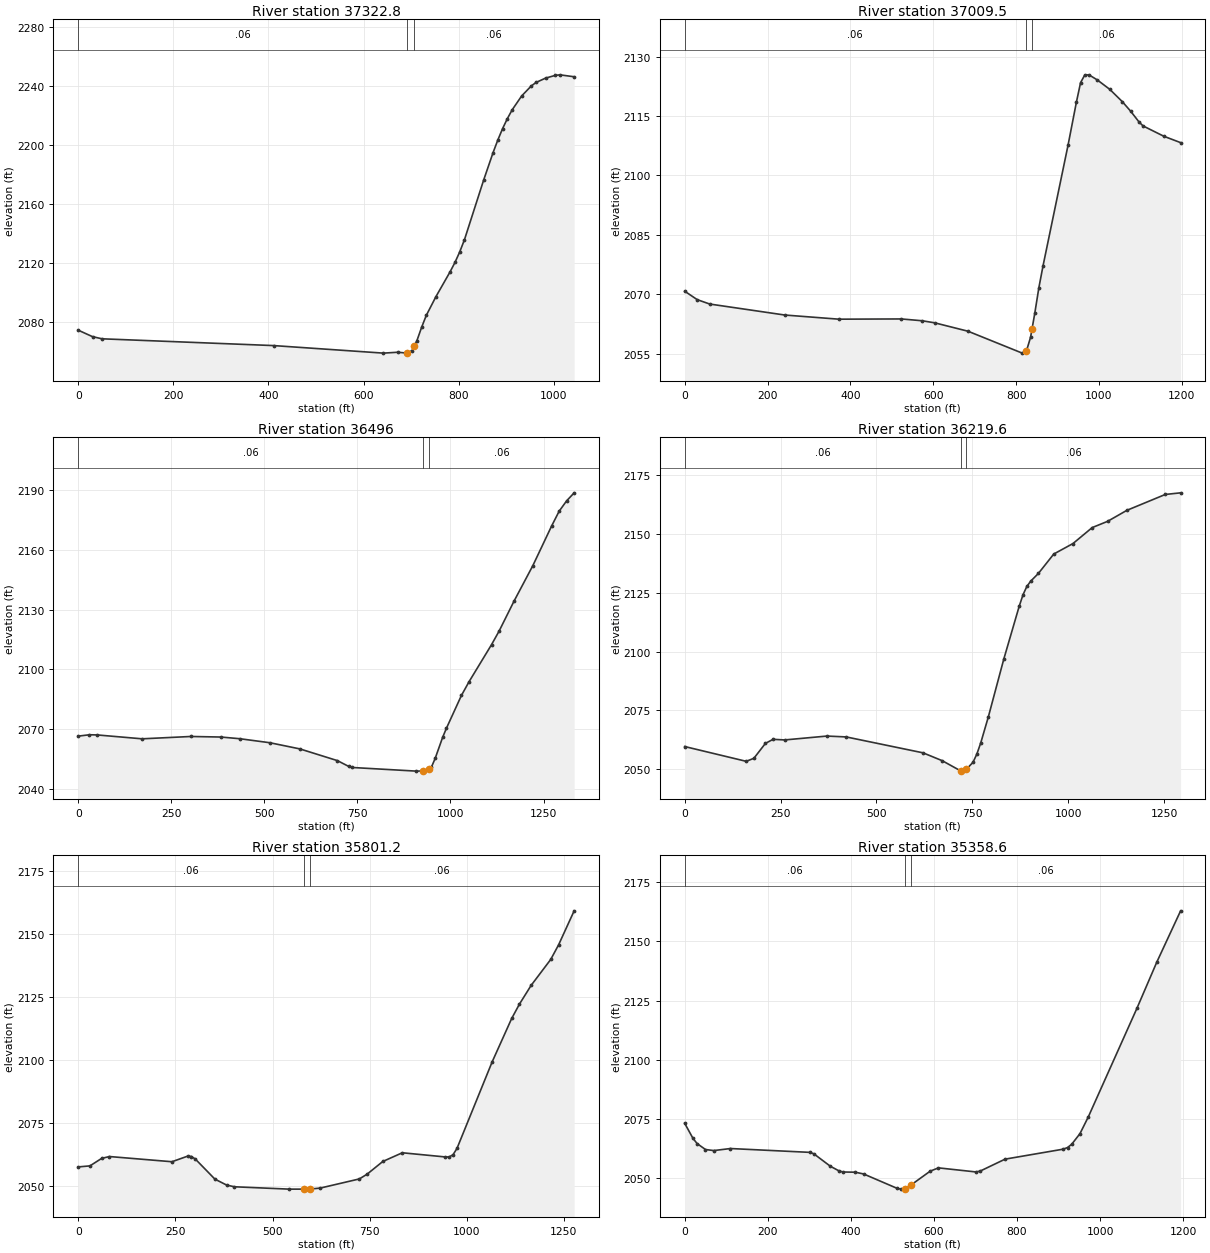
Type RM Length L Ch R = 1 ,37322.8 ,313.1,313.4,313.6
XS GIS Cut Line= 2
     2096240.869      335335.185     2095336.642      334815.877
#Sta/Elev= 30
       0 2074.77    30.1 2070.38    50.1 2068.93   411.1 2064.34   641.7 2059.24
   671.8 2059.84   691.3 2059.26   701.8 2060.94   706.3 2063.85   711.9 2067.48
   721.9 2076.63   731.9 2084.82     752  2097.4   782.1 2114.39   792.1 2120.59
   802.1  2127.7   812.1    2136   852.2 2176.11   872.3 2194.97   882.3 2203.49
   892.3 2211.18   902.4 2217.97   912.4 2223.85   932.4 2233.25   952.5 2239.98
   962.5 2242.34   982.6 2245.29  1002.6 2247.11  1012.7 2247.52  1042.7 2246.21
#Mann= 3 , 0 , 0
       0     .06       0   691.3    .045       0   706.3     .06       0
Bank Sta=691.3,706.3
XS Rating Curve= 0 ,0
Exp/Cntr=0.3,0.1

Type RM Length L Ch R = 1 ,37009.5 ,516.2,513.4,510.5
XS GIS Cut Line= 2
     2096529.837      335168.533     2095502.587      334553.939
#Sta/Elev= 30
       0 2070.82    30.2 2068.69    60.4 2067.58   241.4 2064.81   372.2 2063.76
   523.1 2063.82   573.4 2063.36   603.6 2062.84     684 2060.72   814.8  2055.2
   823.6 2055.65   824.9 2055.72   834.9 2059.19   838.6 2061.39     845  2065.2
     855 2071.73   865.1 2077.27   925.5  2107.7   945.6 2118.52   955.6  2123.4
   965.7 2125.34   975.8 2125.38   995.9  2124.1  1026.1 2121.72  1056.2 2118.63
  1076.4 2116.22  1096.5 2113.52  1106.5 2112.49  1156.8 2109.88  1197.1 2108.28
#Mann= 3 , 0 , 0
       0     .06       0   823.6    .045       0   838.6     .06       0
Bank Sta=823.6,838.6
XS Rating Curve= 0 ,0
Exp/Cntr=0.3,0.1

Type RM Length L Ch R = 1 ,36496   ,275.6,276.3,277
XS GIS Cut Line= 2
     2096896.665      334741.736     2095681.112       334196.24
#Sta/Elev= 30
       0 2066.53    30.3 2067.21    50.5 2067.13   171.6 2065.18   302.8 2066.35
   383.6 2066.07     434 2065.23   514.8 2063.22   595.5 2060.12   696.4 2054.24
   726.7 2051.34   736.8  2050.8   908.4 2048.98   926.8 2049.06   938.7 2049.37
   941.8 2049.85   948.8 2050.94   958.9 2055.35   979.1 2065.96   989.2 2070.49
  1029.5 2086.93  1049.7 2093.74  1110.3 2112.37  1130.5 2119.13  1170.8 2134.22
  1221.3    2152  1271.8 2171.89    1292  2179.3  1312.2 2184.52  1332.3 2188.51
#Mann= 3 , 0 , 0
       0     .06       0   926.8    .045       0   941.8     .06       0
Bank Sta=926.8,941.8
XS Rating Curve= 0 ,0
Exp/Cntr=0.3,0.1

Type RM Length L Ch R = 1 ,36219.6 ,409.6,418.3,422.7
XS GIS Cut Line= 2
     2096915.381      334461.002     2095714.424      333982.092
#Sta/Elev= 30
       0 2059.71   160.4 2053.44   180.4 2054.72   210.5 2061.05   230.5 2062.77
   260.6 2062.51   370.8 2064.15     421 2063.79   621.4 2057.04   671.5  2053.7
   719.6 2049.37   721.6 2049.28   734.6  2050.1   751.7 2053.04   761.7 2056.52
   771.8 2061.23   791.8 2072.38   831.9 2096.79     872 2119.16     882 2124.07
     892 2127.61     902 2129.84   922.1 2133.13   962.2 2141.36  1012.3 2145.81
  1062.4 2152.58  1102.5 2155.22  1152.6 2159.88  1252.8 2166.62  1292.9 2167.32
#Mann= 3 , 0 , 0
       0     .06       0   719.6    .045       0   734.6     .06       0
Bank Sta=719.6,734.6
XS Rating Curve= 0 ,0
Exp/Cntr=0.3,0.1

Type RM Length L Ch R = 1 ,35801.2 ,452.1,441.8,424.9
XS GIS Cut Line= 2
     2096937.722      334125.892     2095773.338      333603.359
#Sta/Elev= 30
       0 2057.68    30.2 2058.09    60.3 2061.05    80.4 2061.79   241.2 2059.73
   281.4 2061.93   291.4  2061.8   301.5 2060.78   351.7 2052.85   381.9 2050.49
     402 2049.81   542.7 2048.88   580.6 2048.88   595.6 2048.89     623  2049.3
   723.6 2052.92   743.6 2054.82   783.8 2059.83   834.1 2063.28   944.6 2061.63
   954.7 2061.63   964.7 2062.53   974.8 2065.02  1065.2 2099.26  1115.5 2116.47
  1135.6 2122.19  1165.7 2129.61    1216 2139.86  1236.1 2145.59  1276.3 2159.12
#Mann= 3 , 0 , 0
       0     .06       0   580.6    .045       0   595.6     .06       0
Bank Sta=580.6,595.6
XS Rating Curve= 0 ,0
Exp/Cntr=0.3,0.1

Type RM Length L Ch R = 1 ,35358.6 ,506.3,508.2,513.6
XS GIS Cut Line= 3
     2096973.623      333587.373     2095953.359      333532.716
     2095794.752      333465.698
#Sta/Elev= 30
       0 2073.26      20 2066.88      30 2064.68    50.1 2062.18    70.1 2061.74
   110.2  2062.6   300.5 2060.99   310.5 2060.43   350.6 2055.13   370.6 2053.25
   380.6  2052.7   410.7 2052.61   430.7 2051.87   510.9 2045.84   520.9 2045.47
   529.6 2045.64   544.6 2047.18     591 2053.05     611 2054.44   701.2 2052.72
   711.2 2053.07   771.3 2058.12   911.5 2062.34   921.6 2063.02   931.6 2064.38
   951.6 2068.88   971.6 2075.92  1088.7 2121.76  1136.5 2141.23  1193.9  2162.9
#Mann= 3 , 0 , 0
       0     .06       0   529.6    .045       0   544.6     .06       0
Bank Sta=529.6,544.6
XS Rating Curve= 0 ,0
Exp/Cntr=0.3,0.1

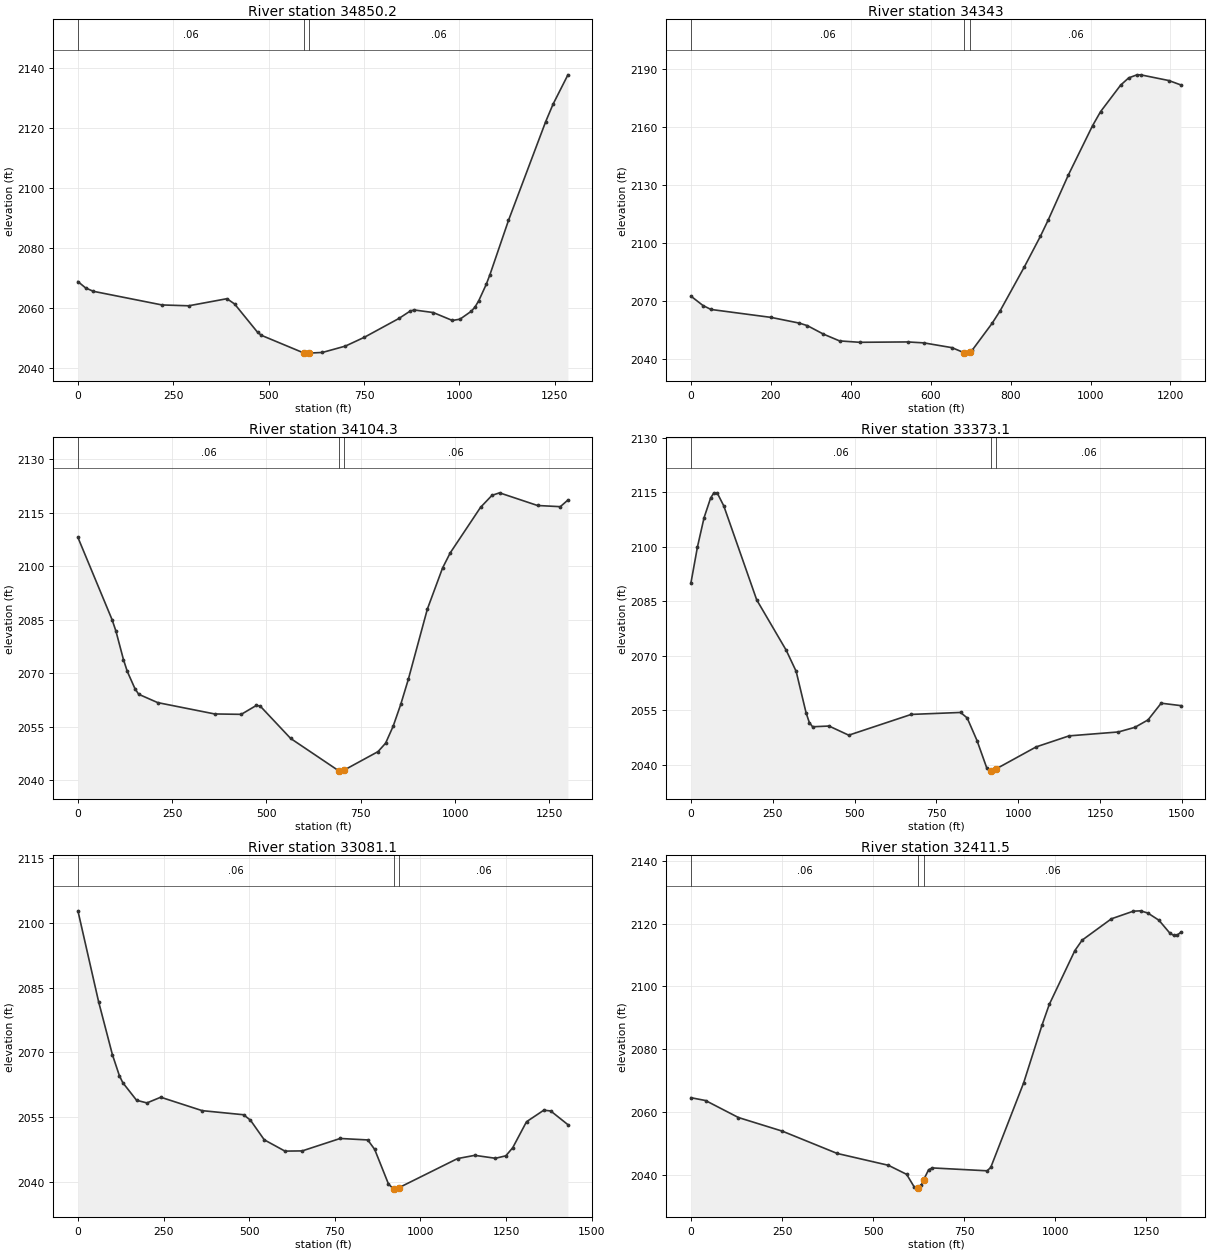
Type RM Length L Ch R = 1 ,34850.2 ,497.5,506.9,516.3
XS GIS Cut Line= 3
     2097103.647      333176.269     2096083.383      333121.612
      2095869.23      333274.034
#Sta/Elev= 30
       0  2068.9      20 2066.79    40.1 2065.66   220.4 2061.11   290.5 2060.83
   390.7 2063.19   410.7 2061.44   470.8 2052.04   480.8 2051.01   591.6 2045.15
     601 2045.07   606.6 2045.08   641.1  2045.3   701.2 2047.41   751.3 2050.37
   841.4  2056.6   871.5 2059.11   881.5 2059.44   931.6 2058.58   981.7 2055.94
  1001.7 2056.38  1031.5 2059.03  1041.2 2060.46  1050.9 2062.53  1070.4 2067.95
  1080.1 2071.17  1128.8 2089.26  1226.2  2122.1  1245.6 2127.94  1284.6 2137.72
#Mann= 3 , 0 , 0
       0     .06       0   591.6    .045       0   606.6     .06       0
Bank Sta=591.6,606.6
XS Rating Curve= 0 ,0
Exp/Cntr=0.3,0.1

Type RM Length L Ch R = 1 ,34343   ,239.5,238.7,237.8
XS GIS Cut Line= 2
     2097165.909      332982.327     2096071.625      332429.172
#Sta/Elev= 30
       0 2072.39    30.2 2067.51    50.2 2065.46     201 2061.33   271.4 2058.37
   291.5 2057.06   331.7 2052.66   371.9 2049.15   422.1 2048.42   542.7 2048.61
   582.9 2048.12   653.3 2045.64   684.1 2042.97   693.5  2042.8   699.1 2043.59
   703.5 2044.21   753.8 2058.29   773.9  2064.8   834.2 2087.48   874.4 2103.37
   894.5 2112.06   944.7 2135.33    1005  2160.8  1025.1 2168.11  1075.4  2181.9
  1095.5 2185.64  1115.6 2187.18  1125.6 2187.23    1196 2184.26  1226.2 2181.97
#Mann= 3 , 0 , 0
       0     .06       0   684.1    .045       0   699.1     .06       0
Bank Sta=684.1,699.1
XS Rating Curve= 0 ,0
Exp/Cntr=0.3,0.1

Type RM Length L Ch R = 1 ,34104.3 ,738.1,731,721.9
XS GIS Cut Line= 2
     2097311.681      332768.225     2096135.333      332216.812
#Sta/Elev= 30
       0 2108.04    90.6 2084.99   100.7 2081.82   120.8  2073.8   130.9  2070.5
   151.1  2065.7   161.1  2064.1   211.5 2061.76   362.6 2058.58   433.1 2058.47
   473.3 2060.98   483.4 2060.78     564 2051.72   691.7 2042.64   694.9 2042.56
   706.7  2042.9   795.6 2048.02   815.8 2050.39   835.9 2055.16     856 2061.28
   876.2 2068.33   926.5 2087.96   966.8 2099.47     987 2103.69  1067.5 2116.47
  1097.8 2119.83  1117.9 2120.54  1218.6 2116.99    1279 2116.66  1299.2 2118.52
#Mann= 3 , 0 , 0
       0     .06       0   691.7    .045       0   706.7     .06       0
Bank Sta=691.7,706.7
XS Rating Curve= 0 ,0
Exp/Cntr=0.3,0.1

Type RM Length L Ch R = 1 ,33373.1 ,290.8,292,293.3
XS GIS Cut Line= 3
     2097710.428      331929.957      2096429.78      331810.271
     2096233.775      331888.673
#Sta/Elev= 30
       0 2090.04    20.1 2100.04    40.2 2108.04    60.3 2113.48    70.3 2114.89
    80.4 2114.85   100.5 2111.28     201 2085.42   291.4  2071.5   321.6 2065.72
   351.7 2054.38   361.8 2051.63   371.8 2050.46     422 2050.66   482.3 2048.14
   673.3 2053.86     824  2054.4   844.1  2052.9   874.2 2046.67   904.4 2039.02
   914.4 2038.24   917.9  2038.3   932.9 2038.87  1055.1 2044.92  1155.6 2047.95
  1306.3 2049.03  1356.6  2050.3  1396.8 2052.35    1437 2056.95  1497.3 2056.28
#Mann= 3 , 0 , 0
       0     .06       0   917.9    .045       0   932.9     .06       0
Bank Sta=917.9,932.9
XS Rating Curve= 0 ,0
Exp/Cntr=0.3,0.1

Type RM Length L Ch R = 1 ,33081.1 ,676,669.5,670.2
XS GIS Cut Line= 2
     2097705.875      331685.656     2096286.831      331504.798
#Sta/Elev= 30
       0  2102.8    60.4 2081.74   100.7 2069.46   120.9 2064.63     131 2062.97
   171.3 2058.89   201.5 2058.28   241.8  2059.6   362.7 2056.49   483.6 2055.54
   503.7 2054.28     544 2049.73   604.4 2047.11   654.8 2047.16   765.6 2050.04
   846.2  2049.7   866.4  2047.5   906.7 2039.47   921.8 2038.32   926.8  2038.3
   936.8 2038.62  1108.2 2045.38  1158.5 2046.13    1219 2045.45  1249.2 2046.02
  1269.3 2047.89  1309.6 2053.92    1360 2056.59  1380.2 2056.42  1430.5 2053.24
#Mann= 3 , 0 , 0
       0     .06       0   921.8    .045       0   936.8     .06       0
Bank Sta=921.8,936.8
XS Rating Curve= 0 ,0
Exp/Cntr=0.3,0.1

Type RM Length L Ch R = 1 ,32411.5 ,909.1,913.2,900.6
XS GIS Cut Line= 2
     2097695.448      331126.031       2096364.5      330935.231
#Sta/Elev= 30
       0 2064.54    40.1 2063.64   130.4 2058.22   250.8 2053.88   401.4 2046.77
   541.8    2043     592 2040.11   612.1 2036.21   622.1  2035.4   624.1 2035.63
   632.1 2036.57   639.1 2038.46   652.2 2041.58   662.2 2042.16   812.8 2041.24
   822.8 2042.32   913.1 2069.28   963.3 2087.62   983.3 2094.25  1053.6 2111.43
  1073.6 2114.76  1153.9 2121.56  1214.1 2123.99  1234.2  2124.1  1254.2 2123.37
  1284.4 2121.09  1314.4 2116.97  1324.5  2116.3  1334.5 2116.37  1344.6 2117.28
#Mann= 3 , 0 , 0
       0     .06       0   624.1    .045       0   639.1     .06       0
Bank Sta=624.1,639.1
XS Rating Curve= 0 ,0
Exp/Cntr=0.3,0.1

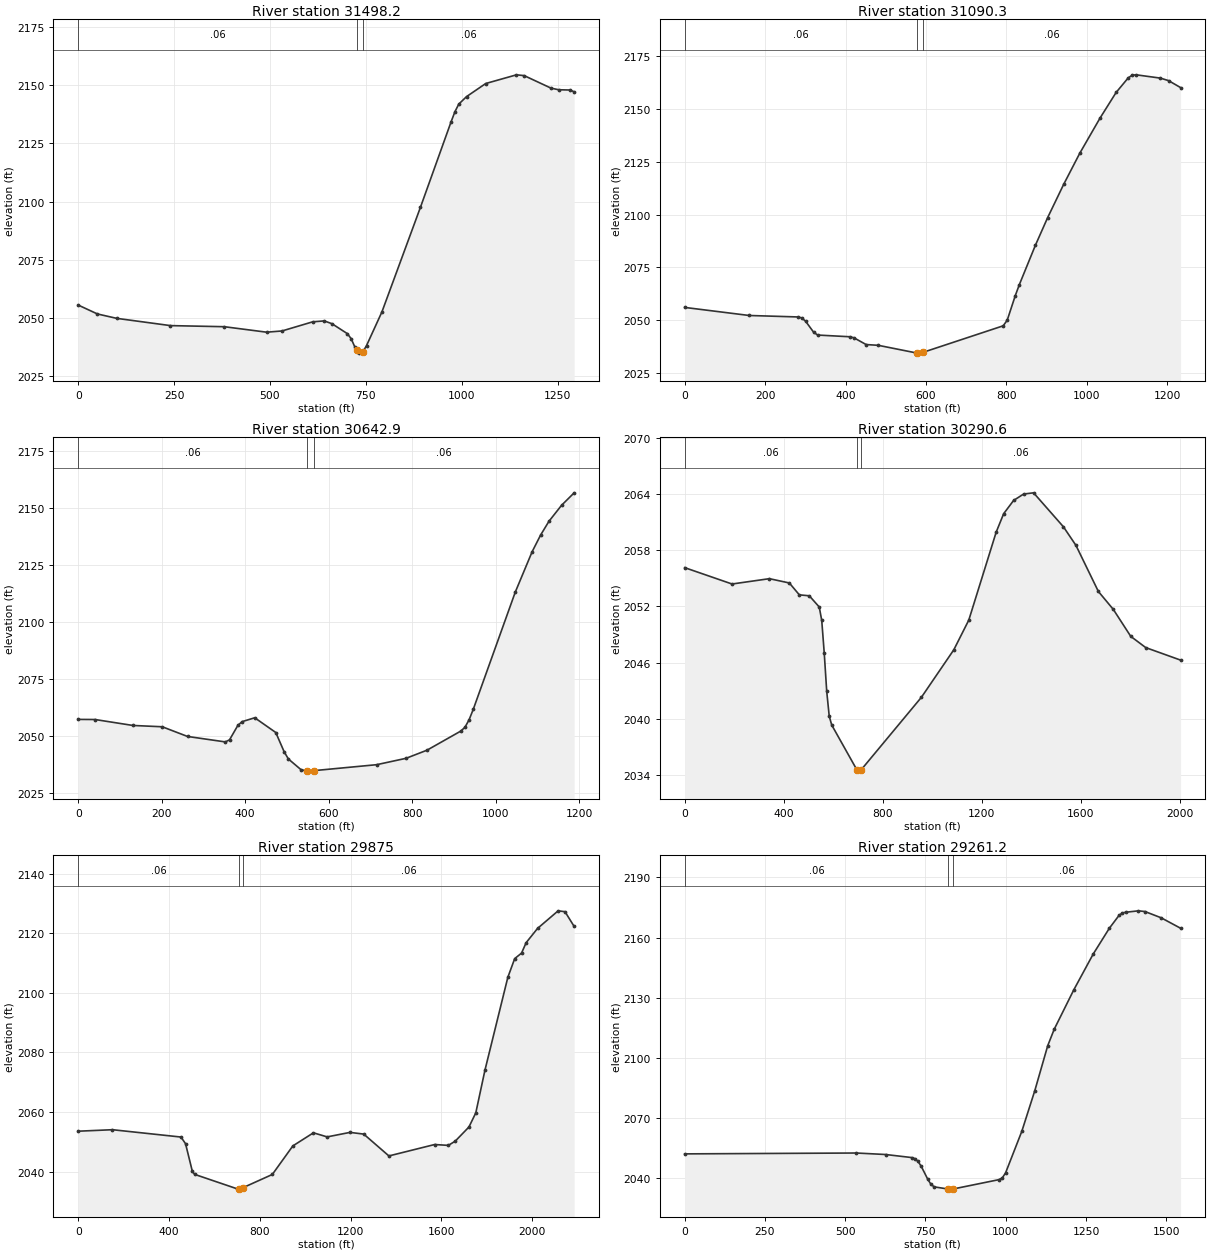
Type RM Length L Ch R = 1 ,31498.2 ,408.5,407.9,407.3
XS GIS Cut Line= 2
      2097689.12      330786.434     2096402.061      330659.781
#Sta/Elev= 30
       0  2055.6    50.1 2051.78   100.2  2049.9   240.6 2046.78     381 2046.31
   491.2 2043.96   531.4 2044.48   611.6 2048.41   641.6  2048.8   661.7  2047.6
   701.8 2043.34   711.8 2041.16   721.8 2037.45   727.2 2036.11   731.8 2034.97
   742.2 2035.47   751.9 2038.22     792 2052.66   892.3 2097.49   972.5 2134.31
   982.5 2138.63   992.5 2141.86  1012.6 2145.06  1062.7 2150.69  1142.9 2154.42
    1163 2154.08  1233.1  2148.7  1253.2 2148.01  1283.2  2147.9  1293.3 2147.11
#Mann= 3 , 0 , 0
       0     .06       0   727.2    .045       0   742.2     .06       0
Bank Sta=727.2,742.2
XS Rating Curve= 0 ,0
Exp/Cntr=0.3,0.1

Type RM Length L Ch R = 1 ,31090.3 ,452,447.2,441.8
XS GIS Cut Line= 2
     2097681.142      330358.305     2096448.245      330321.097
#Sta/Elev= 30
       0 2056.06   160.4 2052.24   280.8 2051.55   290.8 2051.13   300.8 2049.51
   320.9 2044.26   330.9 2042.97   411.2 2042.16   421.2 2041.65   451.3 2038.47
   481.4 2038.11   578.1 2034.43   581.6 2034.41   593.1  2034.8   792.2 2047.35
   802.2    2050   822.3 2061.65   832.3 2066.82   872.4 2085.54   902.5 2098.48
   942.6 2114.34   982.8 2129.13  1032.9 2145.69    1073 2157.86  1103.1 2164.77
  1113.1 2166.07  1123.2 2166.23  1183.3 2164.67  1203.4 2163.49  1233.5 2160.18
#Mann= 3 , 0 , 0
       0     .06       0   578.1    .045       0   593.1     .06       0
Bank Sta=578.1,593.1
XS Rating Curve= 0 ,0
Exp/Cntr=0.3,0.1

Type RM Length L Ch R = 1 ,30642.9 ,355.3,352.4,349.4
XS GIS Cut Line= 2
     2097671.373      329833.999      2096493.31       329990.62
#Sta/Elev= 30
       0 2057.16    40.3 2057.11   130.9  2054.5   201.4 2053.92   261.9 2049.66
   352.5 2047.26   362.6 2048.18   382.7 2054.57   392.8 2056.18     423 2057.88
   473.4  2051.4   493.5 2042.92   503.6 2039.76   533.8 2035.06   548.9 2034.42
   553.9 2034.41   563.9 2034.61   715.1 2037.24   785.6 2040.05   835.9 2043.63
   916.5    2052   926.6 2053.66   936.6 2056.97   946.7 2061.62  1047.4 2113.19
  1087.7 2130.91  1107.9 2138.21    1128  2144.3  1158.2 2151.33  1188.4 2156.82
#Mann= 3 , 0 , 0
       0     .06       0   548.9    .045       0   563.9     .06       0
Bank Sta=548.9,563.9
XS Rating Curve= 0 ,0
Exp/Cntr=0.3,0.1

Type RM Length L Ch R = 1 ,30290.6 ,410.5,415.6,420.6
XS GIS Cut Line= 2
     2097663.317      329401.705     2095731.021      329930.711
#Sta/Elev= 30
       0 2056.15   191.3  2054.4   342.3 2054.97   422.8 2054.51   463.1 2053.24
   503.4 2053.14   543.6 2051.94   553.7  2050.5   563.8 2047.01   573.8 2042.91
   583.9 2040.27     594 2039.32   696.6 2034.48   704.7 2034.39   711.6 2034.49
   956.4 2042.29  1087.3 2047.37  1147.7 2050.54  1258.4 2059.95  1288.6 2061.92
  1328.9 2063.34  1369.2 2064.02  1409.4 2064.15  1530.2 2060.51  1580.6 2058.53
  1671.2  2053.6  1731.6 2051.68    1802  2048.8  1862.5  2047.6  2003.4 2046.26
#Mann= 3 , 0 , 0
       0     .06       0   696.6    .045       0   711.6     .06       0
Bank Sta=696.6,711.6
XS Rating Curve= 0 ,0
Exp/Cntr=0.3,0.1

Type RM Length L Ch R = 1 ,29875   ,610.3,613.8,617.2
XS GIS Cut Line= 3
     2097658.605      329148.818     2096593.222       329191.41
     2095520.539      329507.558
#Sta/Elev= 30
       0 2053.54   150.9 2054.04   452.6 2051.58   472.8 2049.34   502.9 2040.02
     513 2039.05   704.1  2034.1   709.2 2034.18   724.2 2034.53     855 2039.02
   945.5 2048.61  1036.1    2053  1096.5 2051.63  1197.2 2053.14  1257.7 2052.57
  1368.5 2045.24    1570 2049.07  1630.4 2048.78  1660.6  2050.2  1721.1 2054.95
  1751.3  2059.7  1791.6 2074.03  1892.4 2105.19  1922.6 2111.46  1952.8 2113.31
    1973 2116.81  2023.3  2121.6    2114  2127.5  2144.2 2127.21  2184.5 2122.26
#Mann= 3 , 0 , 0
       0     .06       0   709.2    .045       0   724.2     .06       0
Bank Sta=709.2,724.2
XS Rating Curve= 0 ,0
Exp/Cntr=0.3,0.1

Type RM Length L Ch R = 1 ,29261.2 ,673.5,672.7,660.8
XS GIS Cut Line= 2
     2097649.794      328675.976     2096112.525      328524.701
#Sta/Elev= 30
       0 2051.91   535.1 2052.34     626 2051.59   706.7 2050.08   716.8 2049.54
   726.9 2048.14     737 2045.65   757.2  2039.2   767.3 2036.64   777.4 2035.42
   821.1 2034.34   827.9  2034.3   836.1 2034.37   979.3 2039.05   989.4 2039.95
   999.5 2042.41    1050 2063.15  1090.4 2083.42  1130.8 2105.96    1151 2114.18
  1211.5 2133.71  1272.1 2151.65  1322.6  2164.6  1352.9 2171.05    1363 2172.23
  1373.1 2172.61  1413.4 2173.33  1433.6 2172.98  1484.1 2169.85  1544.7 2164.62
#Mann= 3 , 0 , 0
       0     .06       0   821.1    .045       0   836.1     .06       0
Bank Sta=821.1,836.1
XS Rating Curve= 0 ,0
Exp/Cntr=0.3,0.1

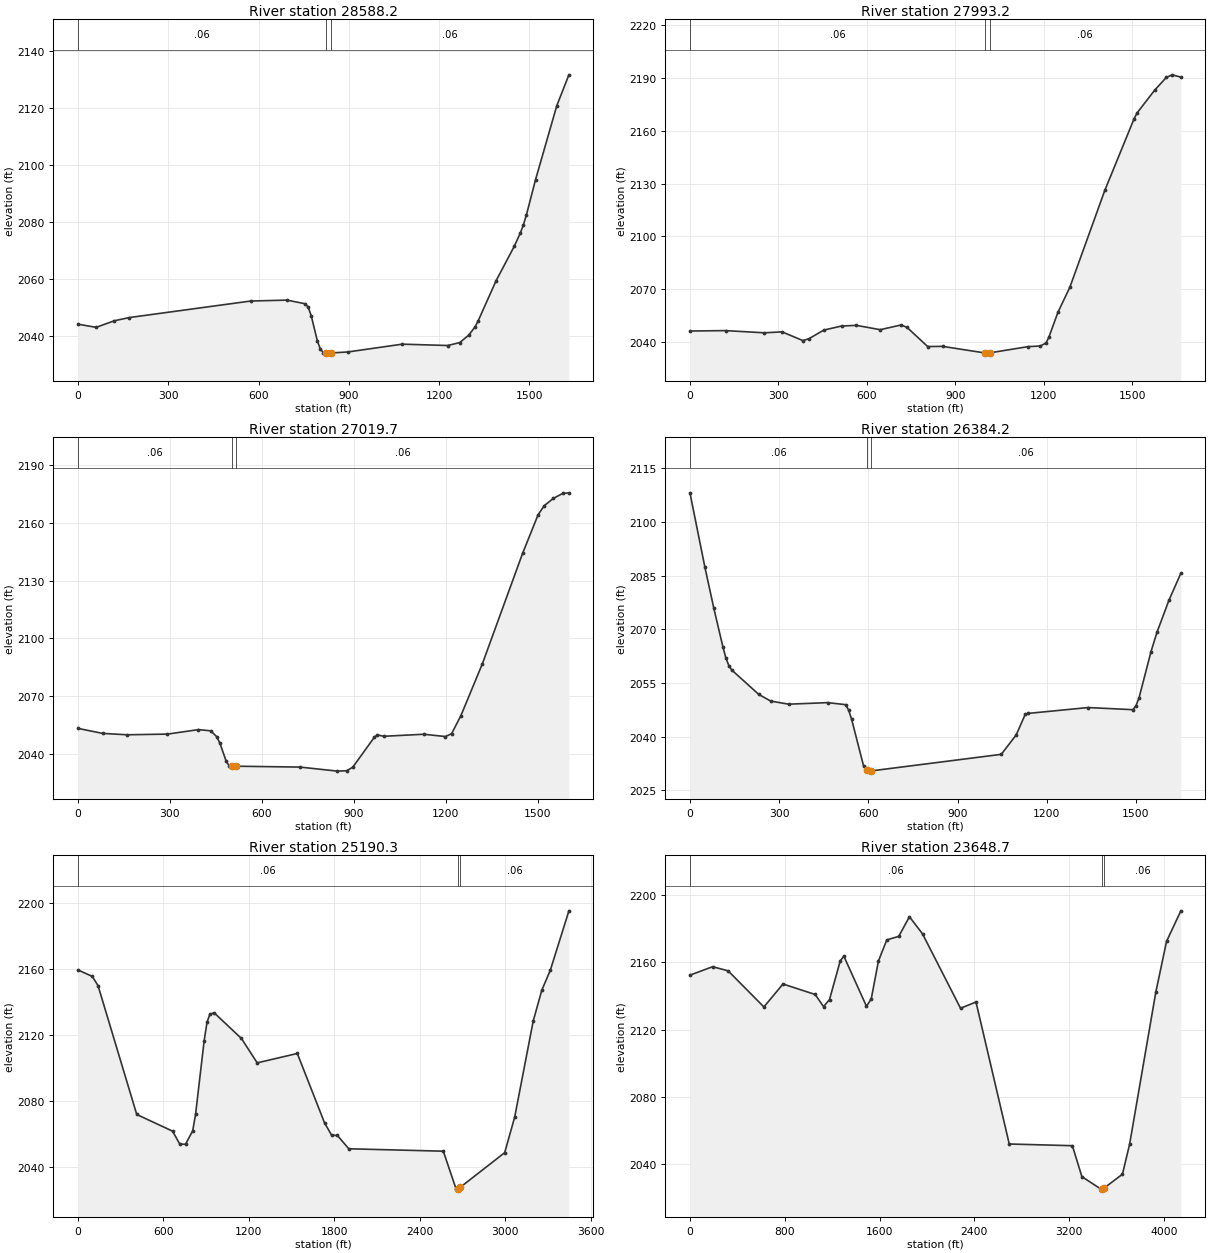
Type RM Length L Ch R = 1 ,28588.2 ,579,595,610.3
XS GIS Cut Line= 2
     2097906.404      328298.613     2096282.812      328139.526
#Sta/Elev= 30
       0 2044.25    60.4 2043.14   120.8 2045.44   171.2 2046.58     574 2052.36
   694.8 2052.68   755.3 2051.39   765.3 2050.18   775.4 2047.11   795.5 2038.39
   805.6 2035.48   815.7 2034.29   825.5 2034.12   825.8 2034.11   840.5 2034.17
   896.2 2034.51  1077.5 2037.25  1228.6 2036.78  1268.8 2037.81    1299 2040.45
  1319.2 2043.28  1329.3 2045.27  1389.7 2059.52  1450.1 2071.58  1470.2 2076.24
  1480.3 2079.04  1490.4  2082.6  1520.6 2094.89  1591.1 2120.75  1631.4 2131.59
#Mann= 3 , 0 , 0
       0     .06       0   825.5    .045       0   840.5     .06       0
Bank Sta=825.5,840.5
XS Rating Curve= 0 ,0
Exp/Cntr=0.3,0.1

Type RM Length L Ch R = 1 ,27993.2 ,992.4,973,778.3
XS GIS Cut Line= 4
     2098042.511      328162.506     2097361.435      327910.147
     2096941.365      327535.784     2096566.574      327497.685
#Sta/Elev= 30
       0 2046.09     121 2046.32   252.2 2045.07   312.7 2045.61   383.3 2040.64
   403.5 2041.69     454 2046.61   514.5 2048.94   564.9  2049.3   645.6 2046.84
   716.2 2049.52   736.4 2048.18   806.7 2037.25     857 2037.36    1002 2033.58
  1007.7 2033.51    1017 2033.66  1148.3 2037.23  1188.5 2037.54  1208.6 2039.32
  1218.7 2042.96  1248.8 2056.83    1289 2070.96    1408 2126.25  1507.1 2166.89
    1517  2170.1  1576.5 2183.04  1616.2 2190.32    1636 2191.82  1665.7 2190.52
#Mann= 3 , 0 , 0
       0     .06       0    1002    .045       0    1017     .06       0
Bank Sta=1002,1017
XS Rating Curve= 0 ,0
Exp/Cntr=0.3,0.1

Type RM Length L Ch R = 1 ,27019.7 ,629.3,634.5,462.1
XS GIS Cut Line= 2
     2098218.649      327522.005     2096625.083      327365.342
#Sta/Elev= 30
       0  2053.2    80.6  2050.6   161.1 2049.88     292 2050.24   392.8 2052.56
     433 2051.95   453.2 2048.79   463.2 2045.39   483.4 2036.16   493.5 2033.66
     501 2033.44     516 2033.55   725.1 2033.09   845.9 2030.99   876.2 2031.19
   896.3 2033.03   966.8 2048.63   976.9 2049.85     997  2049.1  1127.9 2050.16
  1198.4 2048.97  1218.6 2050.46  1248.8 2059.77  1319.3 2086.91  1450.2  2144.2
  1500.5 2164.15  1520.7 2168.96  1550.9  2172.8  1581.1 2175.32  1601.2 2175.65
#Mann= 3 , 0 , 0
       0     .06       0     501    .045       0     516     .06       0
Bank Sta=501,516
XS Rating Curve= 0 ,0
Exp/Cntr=0.3,0.1

Type RM Length L Ch R = 1 ,26384.2 ,1185.9,1192.7,1177.1
XS GIS Cut Line= 2
     2098384.948      327267.751     2096742.326      327100.151
#Sta/Elev= 30
       0 2108.11    50.3 2087.35    80.5 2075.82   110.8 2065.12   120.8 2062.02
   130.9 2059.84     141 2058.59   231.6  2051.8   271.8 2049.94   332.2 2049.08
   463.1 2049.51   523.5 2048.95   533.6 2047.45   543.7 2044.89   583.9 2031.88
   594.5 2030.57   604.1 2030.38   609.5 2030.44  1047.1 2035.07  1097.4  2040.5
  1127.6  2046.2  1137.7  2046.5    1339 2048.14  1490.1 2047.54  1500.1 2048.63
  1510.2 2050.75  1550.5 2063.68  1570.6  2069.1  1610.9 2078.07  1651.2 2085.66
#Mann= 3 , 0 , 0
       0     .06       0   594.5    .045       0   609.5     .06       0
Bank Sta=594.5,609.5
XS Rating Curve= 0 ,0
Exp/Cntr=0.3,0.1

Type RM Length L Ch R = 1 ,25190.3 ,1542.5,1539.8,1525.6
XS GIS Cut Line= 4
     2099291.487      328506.775     2098558.538      327350.256
     2097666.217       326569.26     2096778.365      326484.871
#Sta/Elev= 30
       0  2159.2   100.7  2155.3     141 2149.67   412.8 2071.56   664.5 2061.44
   714.8 2053.58   755.1 2053.52   805.4 2061.61   825.6 2071.55     886 2116.31
   906.1 2127.47   926.2 2132.42   956.4 2133.21  1147.7 2117.66  1258.5 2102.87
  1540.1 2108.56    1731 2066.54  1781.2 2058.97  1821.4 2058.83  1901.8 2050.76
  2565.1  2049.3  2655.2 2026.29    2668 2026.49    2683 2027.33    2996 2048.41
  3066.1  2069.9  3196.4 2128.25  3256.5 2146.91  3316.6 2159.08  3446.9 2195.07
#Mann= 3 , 0 , 0
       0     .06       0    2668    .045       0    2683     .06       0
Bank Sta=2668,2683
XS Rating Curve= 0 ,0
Exp/Cntr=0.3,0.1

Type RM Length L Ch R = 1 ,23648.7 ,551.6,553.2,554.7
XS GIS Cut Line= 4
     2099635.757      327794.218     2098875.162      326104.897
     2097946.436      325608.509     2096745.044      325906.293
#Sta/Elev= 30
       0 2152.44   191.3 2157.46   322.2 2155.02   624.3 2133.49   785.4 2147.16
  1057.2 2140.91  1127.7 2133.68    1178 2137.92  1268.7 2160.95  1298.9 2163.76
  1490.2 2133.87  1530.4 2138.36  1590.9 2160.81  1661.3 2173.44    1762 2175.54
  1852.6 2187.23    1963 2177.06  2283.9  2132.7  2414.3 2136.44  2695.1 2051.84
  3227.7 2050.82  3308.2 2032.38  3469.2 2024.95  3477.7 2024.97  3492.7 2025.43
  3650.4 2033.84  3710.8 2051.68  3932.1 2142.33  4022.7 2172.59  4143.5 2190.76
#Mann= 3 , 0 , 0
       0     .06       0  3477.7    .045       0  3492.7     .06       0
Bank Sta=3477.7,3492.7
XS Rating Curve= 0 ,0
Exp/Cntr=0.3,0.1