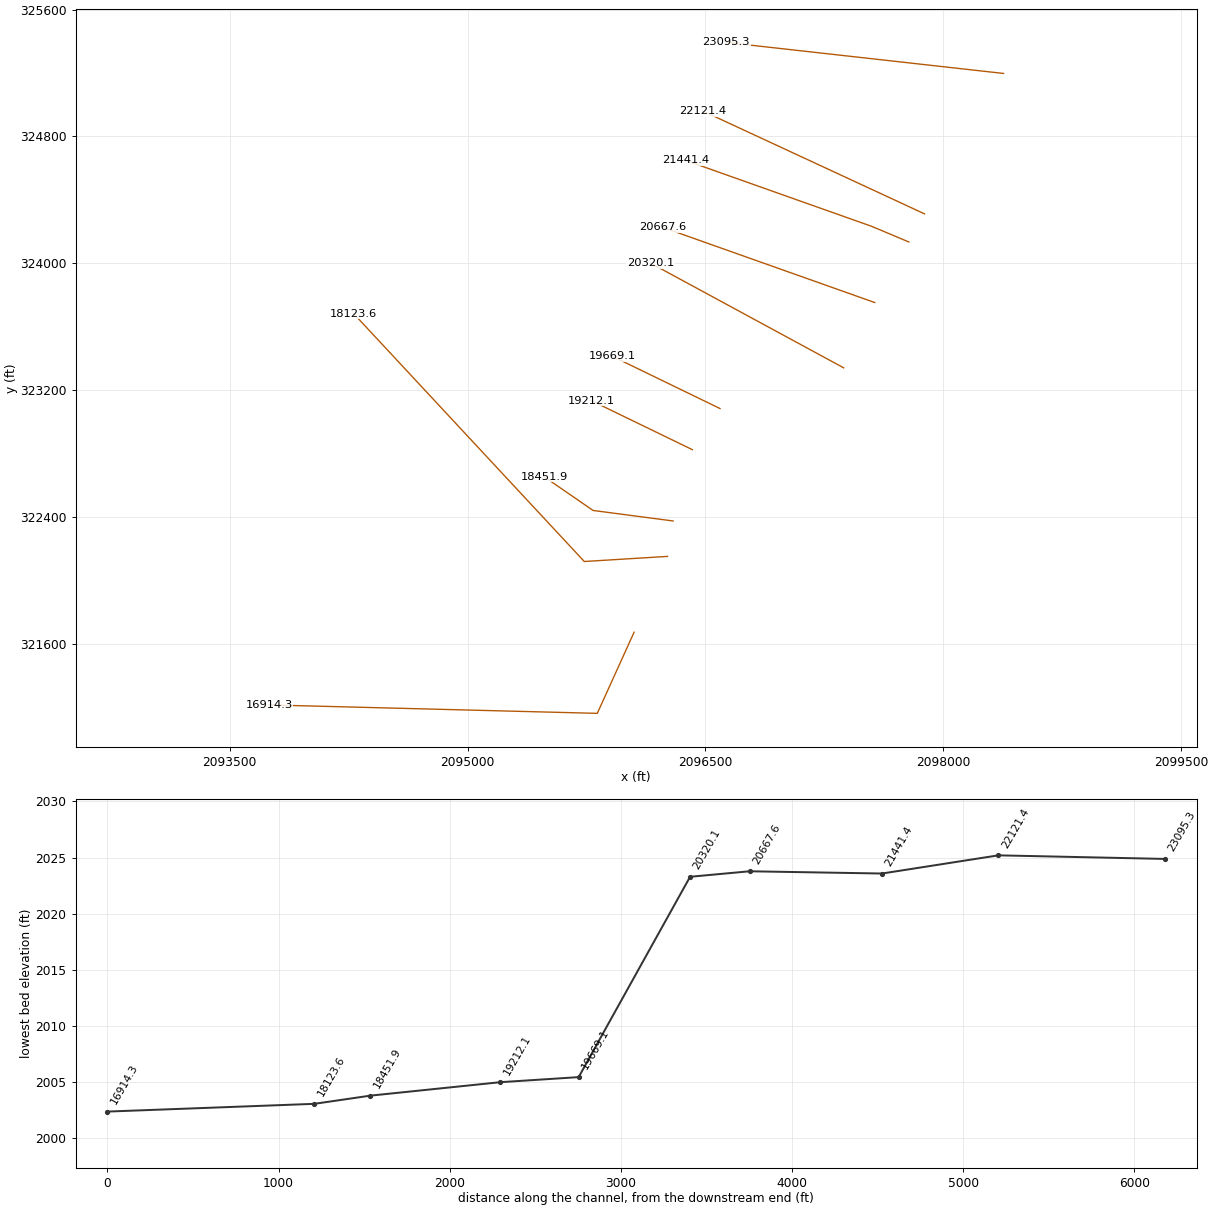
HEC-RAS study HugharCk.prj: HugharCk

--- HugharCk.g01 (geometry) --- (continued)

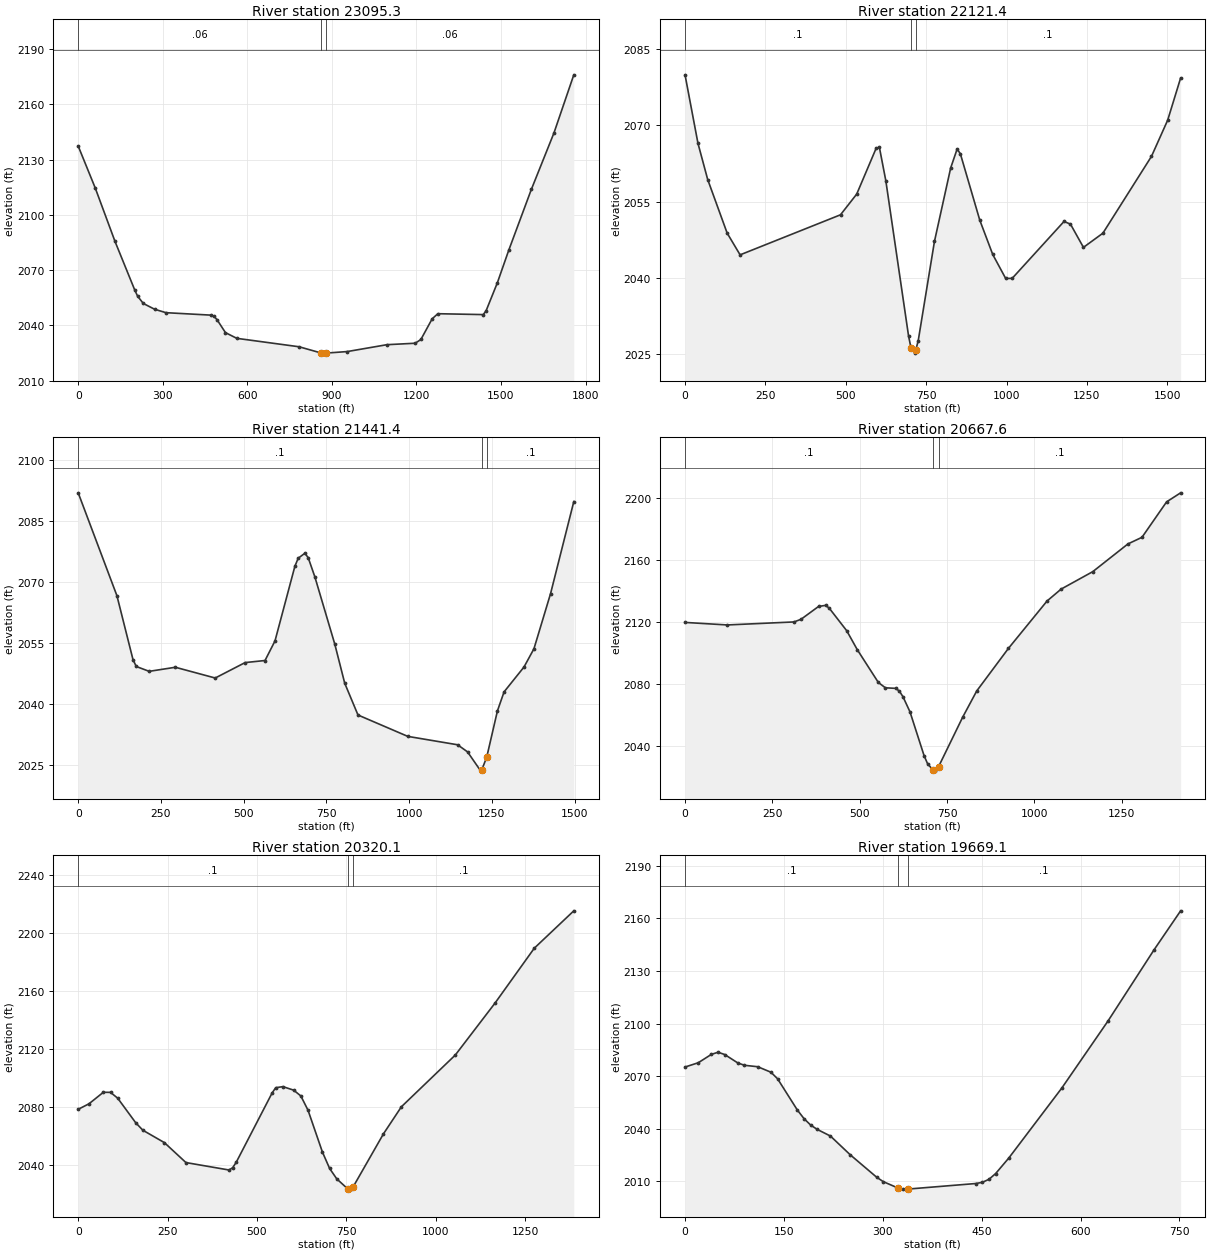
Type RM Length L Ch R = 1 ,23095.3 ,971.3,973.9,966.3
XS GIS Cut Line= 2
     2098379.367      325197.354     2096631.816      325392.733
#Sta/Elev= 30
       0 2137.31    60.3 2114.61   130.6 2085.53     201 2059.01     211 2055.75
   231.1 2051.84   271.3 2048.69   311.5 2046.84   472.3  2045.5   482.3 2044.82
   492.4 2043.07   522.5 2036.01   562.7 2032.91   783.8 2028.33   862.9 2024.91
   874.2 2024.88   877.9 2024.88   954.6 2025.73  1095.3 2029.46  1195.7 2030.25
  1215.8 2032.28    1256 2043.54  1276.1 2046.28  1436.9  2045.8  1446.9 2047.76
  1487.1 2063.04  1527.3 2080.63  1607.7 2113.75  1688.1 2144.48  1758.4 2175.99
#Mann= 3 , 0 , 0
       0     .06       0   862.9    .045       0   877.9     .06       0
Bank Sta=862.9,877.9
XS Rating Curve= 0 ,0
Exp/Cntr=0.3,0.1

Type RM Length L Ch R = 1 ,22121.4 ,669.5,679.9,683
XS GIS Cut Line= 2
     2097881.358      324312.004     2096482.972      324960.605
#Sta/Elev= 30
       0 2079.94    40.3 2066.45    70.5 2059.35     131 2048.81   171.3 2044.53
   483.6 2052.41     534 2056.48   594.4 2065.49   604.5 2065.69   624.6 2059.09
   695.2  2028.6   702.8 2026.23   715.3  2025.2   717.8 2025.81   725.4 2027.68
   775.8 2047.17   826.2 2061.61   846.3 2065.34   856.4 2064.41   916.8 2051.35
   957.1  2044.6   997.4 2039.88  1017.6 2039.91  1178.8  2051.1  1198.9 2050.57
  1239.2    2046  1299.7 2048.79  1450.8  2063.9  1501.2 2071.02  1541.5 2079.32
#Mann= 3 , 0 , 0
       0      .1       0   702.8    .045       0   717.8      .1       0
Bank Sta=702.8,717.8
XS Rating Curve= 0 ,0
Exp/Cntr=0.3,0.1

Type RM Length L Ch R = 1 ,21441.4 ,780.7,773.8,774.1
XS GIS Cut Line= 3
     2097781.864      324135.127     2097548.198      324233.359
      2096375.58      324648.822
#Sta/Elev= 30
       0 2091.91     117 2066.65   165.7 2050.92   175.5 2049.27   214.5 2048.08
   293.6 2049.08     414 2046.44   504.3 2050.23   564.5 2050.74   594.6 2055.54
   654.8  2073.9   664.8 2075.86   684.9 2077.07   694.9    2076     715  2071.3
   775.2 2054.79   805.3 2045.17   845.4 2037.36   995.9 2032.11  1146.4 2030.05
  1176.5  2028.3  1216.6 2023.58  1219.5 2023.89  1234.5 2027.05  1266.8 2038.39
  1286.8 2043.04    1347 2049.14  1377.1 2053.63  1427.3 2067.17  1497.5 2089.76
#Mann= 3 , 0 , 0
       0      .1       0  1219.5    .045       0  1234.5      .1       0
Bank Sta=1219.5,1234.5
XS Rating Curve= 0 ,0
Exp/Cntr=0.3,0.1

Type RM Length L Ch R = 1 ,20667.6 ,350.9,347.5,344.1
XS GIS Cut Line= 2
     2097567.032      323753.203     2096230.316      324227.088
#Sta/Elev= 30
       0 2119.61   120.7 2117.98   311.8 2119.92   331.9 2121.62   382.2 2129.91
   402.3  2130.6   412.4 2128.87   462.7 2114.25   492.9 2102.04   553.2 2080.92
   573.3 2077.48   603.5 2077.11   613.6 2075.26   623.6 2071.76   643.7    2062
     684  2033.8     694 2028.58   710.5 2024.24   714.1 2023.78   725.5 2026.64
   794.6 2058.58   834.8 2075.47   925.4 2102.87    1036 2133.42  1076.2 2141.08
  1166.8 2152.33  1267.4 2170.19  1307.6 2174.46    1378 2197.29  1418.2 2203.12
#Mann= 3 , 0 , 0
       0      .1       0   710.5    .045       0   725.5      .1       0
Bank Sta=710.5,725.5
XS Rating Curve= 0 ,0
Exp/Cntr=0.3,0.1

Type RM Length L Ch R = 1 ,20320.1 ,649,650.9,652.7
XS GIS Cut Line= 2
     2097371.323      323341.494     2096152.786      324002.001
#Sta/Elev= 30
       0  2078.3    30.1 2082.09    70.3 2090.03    90.4 2089.99   110.5 2085.96
   160.7 2069.09   180.8 2063.89     241 2055.35   301.3  2041.6   421.8 2036.47
   431.9 2038.03   441.9 2041.77   542.4 2089.61   552.4 2093.19   572.5 2093.93
   602.6  2091.5   622.7 2087.49   642.8 2077.63     683 2048.84   703.1 2037.54
   723.2 2030.33   753.4 2023.56   763.3 2023.29   768.4 2024.63   853.7  2061.4
   903.9 2080.06  1054.6 2115.71  1165.1 2151.32  1275.6 2189.37    1386  2215.1
#Mann= 3 , 0 , 0
       0      .1       0   753.4    .045       0   768.4      .1       0
Bank Sta=753.4,768.4
XS Rating Curve= 0 ,0
Exp/Cntr=0.3,0.1

Type RM Length L Ch R = 1 ,19669.1 ,449.7,457,459.3
XS GIS Cut Line= 2
     2096591.859      323084.717     2095915.358      323412.986
#Sta/Elev= 30
       0 2075.16      20 2077.59    40.1  2082.4    50.1  2083.6    60.2  2082.3
    80.2 2077.46    90.2 2076.15   110.3 2075.33   130.3  2072.2   140.4 2068.46
   170.4 2050.61   180.5  2045.7   190.5 2042.05   200.5 2039.56   220.6 2035.75
   250.6 2025.06   290.8 2012.22   300.8 2009.71   322.6 2006.15   330.8 2005.44
   337.6 2005.45   441.1 2008.64   451.2 2009.34   461.2 2011.07   471.2 2014.31
   491.3 2023.24   571.5  2063.1   641.7 2101.44   711.8 2142.22   751.9 2164.35
#Mann= 3 , 0 , 0
       0      .1       0   322.6    .045       0   337.6      .1       0
Bank Sta=322.6,337.6
XS Rating Curve= 0 ,0
Exp/Cntr=0.3,0.1

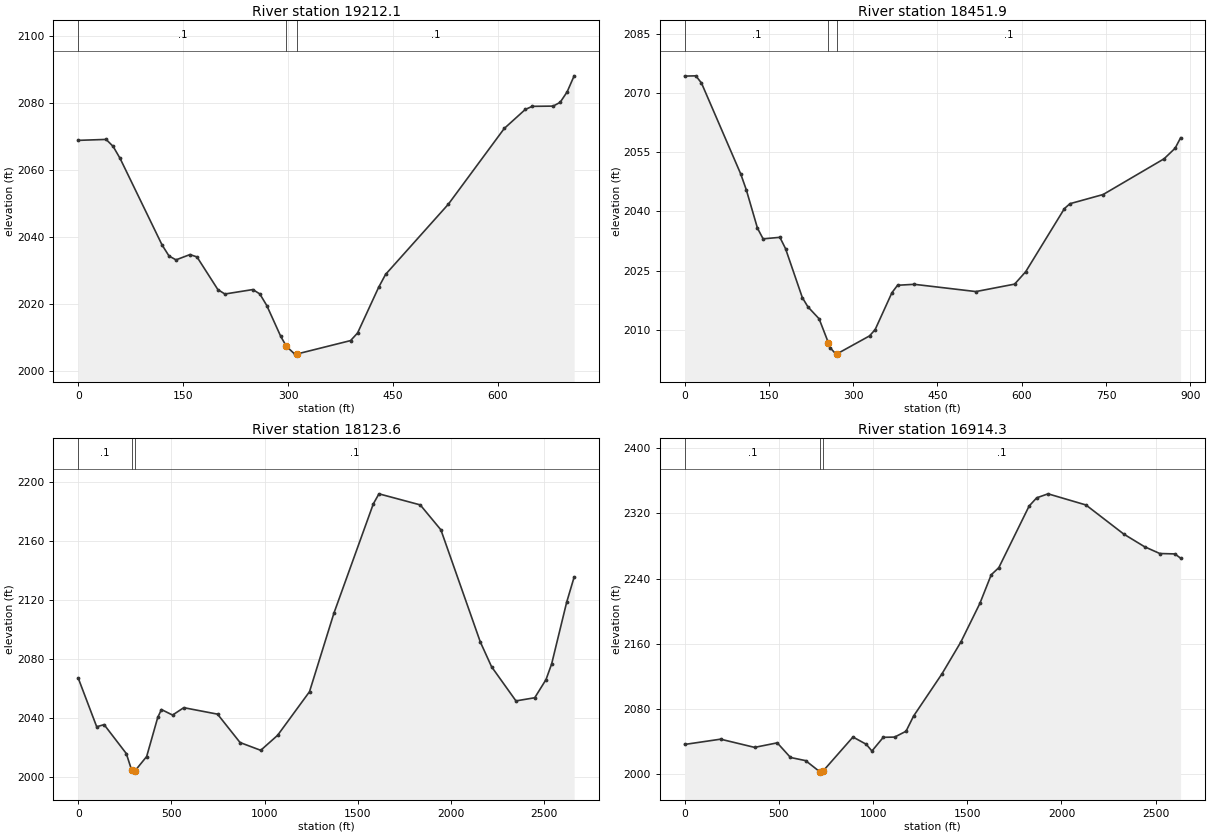
Type RM Length L Ch R = 1 ,19212.1 ,751.9,760,768
XS GIS Cut Line= 2
     2096417.709      322825.323     2095779.851      323134.841
#Sta/Elev= 30
       0 2068.89    39.9 2069.17    49.9 2067.09    59.9 2063.48   119.8 2037.65
   129.8 2034.33   139.8 2033.17   159.8 2034.75   169.8 2034.04   199.7 2024.27
   209.7 2022.96   249.6 2024.29   259.6 2022.99   269.6 2019.51   289.6 2010.27
   297.7  2007.3   309.6 2004.99   312.7 2005.03   389.4 2009.04   399.4 2011.32
   429.4 2024.92   439.4 2028.82   529.2 2049.82   609.1 2072.45   639.1 2078.12
   649.1 2079.06     679 2079.13     689 2080.26     699  2083.4     709 2088.18
#Mann= 3 , 0 , 0
       0      .1       0   297.7    .045       0   312.7      .1       0
Bank Sta=297.7,312.7
XS Rating Curve= 0 ,0
Exp/Cntr=0.3,0.1

Type RM Length L Ch R = 1 ,18451.9 ,322.9,327.8,332.6
XS GIS Cut Line= 3
      2096295.87       322375.98     2095791.664      322442.198
     2095483.439      322654.522
#Sta/Elev= 30
       0 2074.32    19.9 2074.39    29.9 2072.56    99.7 2049.52   109.7 2045.47
   129.6 2035.73   139.6 2033.04   169.5 2033.42   179.5 2030.56   209.4 2018.14
   219.4 2015.78   239.3 2012.75   255.9 2006.64   259.2 2005.38   269.2 2003.79
   270.9 2003.84     329 2008.41     339    2010   368.9 2019.37   378.9 2021.26
   408.8  2021.5   518.4 2019.66   587.3 2021.55     607 2024.69     676 2040.72
   685.8 2041.95   744.9 2044.28   853.3 2053.34     873 2056.02   882.8 2058.68
#Mann= 3 , 0 , 0
       0      .1       0   255.9    .045       0   270.9      .1       0
Bank Sta=255.9,270.9
XS Rating Curve= 0 ,0
Exp/Cntr=0.3,0.1

Type RM Length L Ch R = 1 ,18123.6 ,1209.6,1208.4,1206.8
XS GIS Cut Line= 3
     2096260.991      322152.658      2095736.17      322120.432
     2094282.509      323682.536
#Sta/Elev= 30
       0 2067.02    99.2 2033.89   138.9 2035.36   257.9 2015.69   287.1 2004.18
   297.6 2003.06   302.1 2003.56   367.1 2013.68   426.6 2040.29   446.4 2045.61
     506 2041.86   566.1 2046.88   747.2 2042.48     868 2023.18   978.8 2017.89
  1069.3 2028.09  1240.4 2057.74  1371.3 2111.12  1582.7 2185.45  1612.9 2192.26
  1834.3 2184.73    1945 2167.79  2156.4 2091.58  2216.8 2074.71  2347.6 2051.48
  2448.3 2053.63  2508.7 2065.96  2538.9 2076.58  2619.4  2118.5  2659.7  2135.7
#Mann= 3 , 0 , 0
       0      .1       0   287.1    .045       0   302.1      .1       0
Bank Sta=287.1,302.1
XS Rating Curve= 0 ,0
Exp/Cntr=0.3,0.1

Type RM Length L Ch R = 1 ,16914.3 ,16934.1,16914.9,16889.6
XS GIS Cut Line= 3
      2096049.97      321674.615     2095818.015      321163.124
     2093747.797      321216.317
#Sta/Elev= 30
       0 2036.36   190.6 2042.84   371.1 2032.76   491.4 2038.33   561.6 2020.36
     642 2016.49   718.2 2002.66   722.5 2002.37   733.2 2003.34   893.4 2045.48
   963.8 2036.57   993.9  2028.3  1054.2 2045.13  1114.5  2045.4  1174.9 2052.56
  1215.1 2071.25  1365.9 2123.13  1466.4 2162.34  1566.9 2209.56  1627.2 2244.74
  1667.4 2253.44  1828.3 2329.12  1868.5 2339.22  1928.8 2344.13  2129.9 2330.45
  2330.9 2294.67  2441.5 2279.11    2522 2270.83  2602.4 2270.33  2632.5 2265.06
#Mann= 3 , 0 , 0
       0      .1       0   718.2    .045       0   733.2      .1       0
Bank Sta=718.2,733.2
XS Rating Curve= 0 ,0
Exp/Cntr=0.3,0.1

Chan Stop Cuts=-1
Use User Specified Reach Order=0
Composite Channel Slope=5